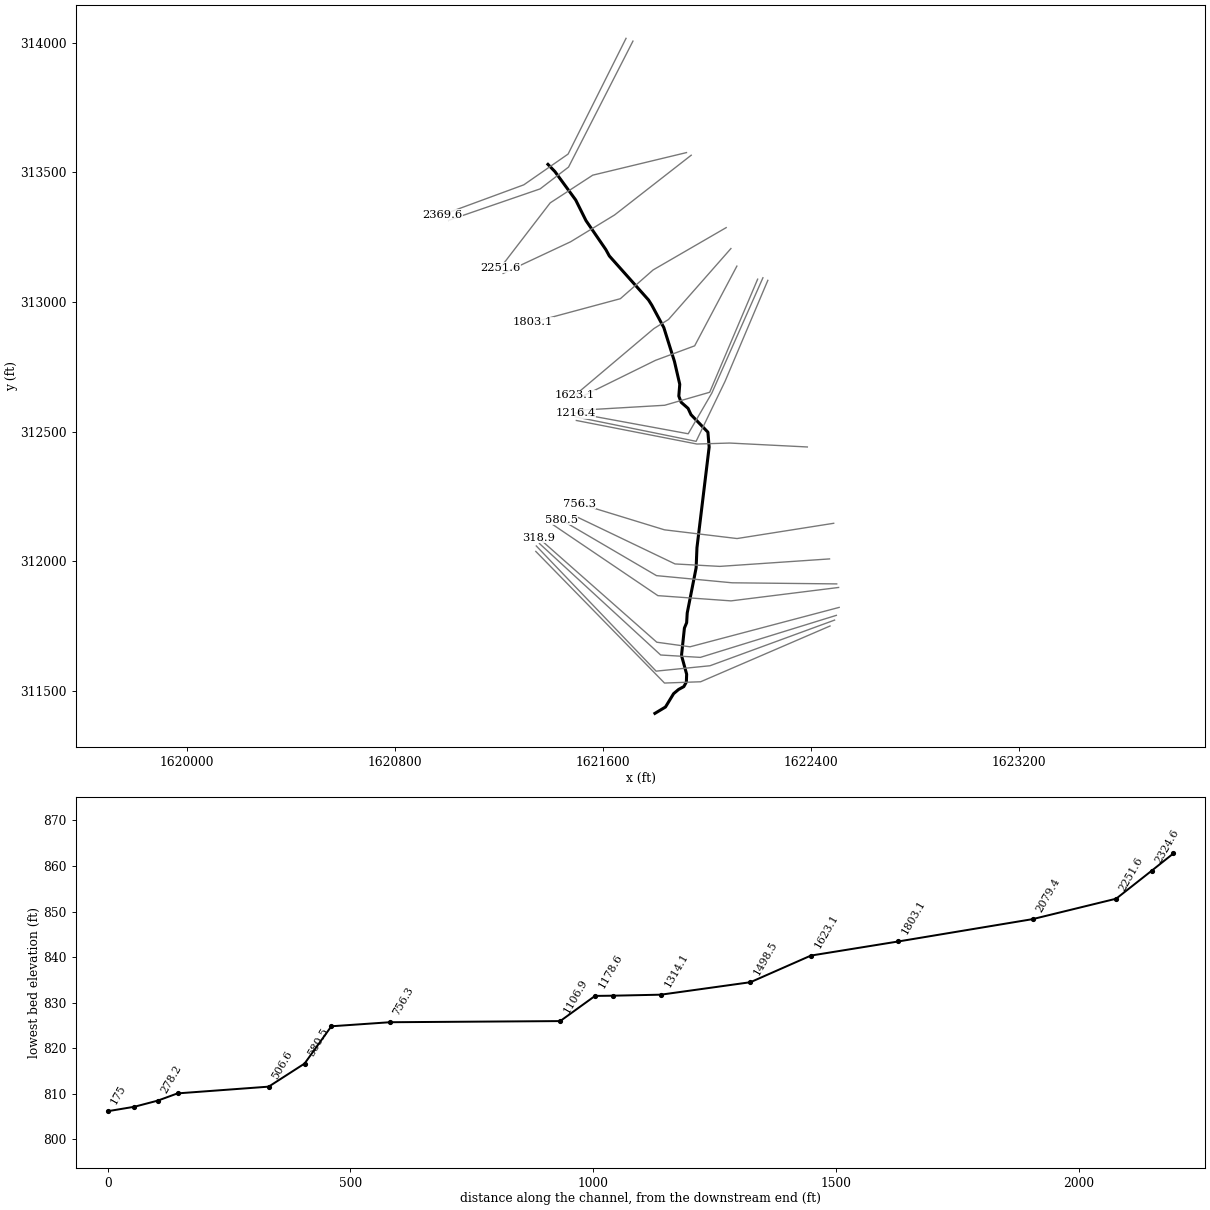
--- lrlbrnch2.prj (project) ---

Proj Title=lrlbrnch2
Current Plan=p01
Default Exp/Contr=0,0
English Units
Geom File=g01
Flow File=f01
Plan File=p01
BEGIN DESCRIPTION:
END DESCRIPTION:
DSS File=dss
DSS Export Rating Curves= 0
DSS Export Rating Curve Sorted= 0
DSS Export Volume Flow Curves= 0
DXF OffsetX= 0
DXF OffsetY= 0
DXF ScaleX= 0
DXF ScaleY= 0

--- lrlbrnch2.p01 (plan) ---

Plan Title=Floodplain
Program Version=4.00
Geom File=g01
Flow File=f01
Subcritical Flow
K Sum by GR= 0
Std Step Tol= 0.01
Critical Tol= 0.01
Num of Std Step Trials= 20
Max Error Tol= 0.3
Flow Tol Ratio= 0.001
Split Flow NTrial= 30
Split Flow Tol= 0.02
Split Flow Ratio= 0.02
Log Output Level= 0
Friction Slope Method= 1
Unsteady Friction Slope Method= 2
Unsteady Bridges Friction Slope Method= 1
Parabolic Critical Depth
Global Vel Dist= 0 , 0 , 0
Global Log Level= 0
CheckData=True
Encroach Param=-1 ,0,0, 0
Run HTab= 0
Run UNet= 0
Run PostProcess= 0
Run WQNet= 0
UNET Theta= 0
UNET Theta Warmup= 0
UNET ZTol= 0
UNET ZSATol= 0
UNET MxIter= 0
UNET MaxInSteps= 0
UNET DtIC= 0
UNET DtMin= 0
UNET MaxCRTS= 0
UNET WFStab= 0
UNET SFStab= 0
UNET WFX= 1
UNET SFX= 1
UNET DSS MLevel= 1
UNET DZMax Abort= 0
UNET Convert EG Bridges= 0
UNET Use Existing IB Tables= 0
UNET Froude Reduction=False
UNET Froude Limit= 0
UNET Froude Power= 0
UNET Time Slicing=0,0, 5
DSS File=dss
Write IC File= 0
Echo Input=False
Echo Output=False
Write Detailed= 0
Detailed Automatic Start=False, 0
WQ ULTIMATE=-1
WQ Max Comp Step=1HOUR
WQ Output Interval=15MIN
WQ Output Selected Increments= 0
WQ Output face flow=0
WQ Output face velocity=0
WQ Output face area=0
WQ Output face dispersion=0
WQ Output cell volume=0
WQ Output cell surface area=0
WQ Output cell continuity=0
WQ Output face conc=0
WQ Output face dconc_dx=0
WQ Output face courant=0
WQ Output face peclet=0
WQ Output face adv mass=0
WQ Output face disp mass=0
WQ Output cell mass=0
WQ Output cell source sink temp=0
WQ Output cell source sink nsm=0
WQ Output MaxMinRange=-1
WQ Daily Max Min Mean=-1
WQ Daily Range=0
WQ Daily Time=0
WQ Create Restart=0
WQ Fixed Restart=0
WQ System Summary=False
Sorting and Armoring Iterations= 10
XS Update Threshold= 0.02
Hydraulics Update Threshold= 0.02
Energy Slope Method= 1
Volume Change Method= 0
XS Weighting Method= 0
Number of US Weighted Cross Sections= 1
Number of DS Weighted Cross Sections= 1
Upstream XS Weight=0.25
Main XS Weight=0.5
Downstream XS Weight=0.25
Number of DS XS's Weighted with US Boundary= 1
Upstream Boundary Weight= 1
Weight of XSs Associated with US Boundary= 0
Number of US XS's Weighted with DS Boundary= 1
Downstream Boundary Weight= 0.5
Weight of XSs Associated with DS Boundary= 0.5
Sediment Output Level= 4
Mass or Volume Output= 0
Output Increment Type= 1
Profile and TS Output Increment= 10
XS Output Flag= 0
XS Output Increment= 10
Disregard all LS=0
Disregard all Conn=0
Disregard all Breaches=0
Disregard all Pumps=0

--- lrlbrnch2.f01 (steady flow) ---

Flow Title=NFF Regression Equation
Program Version=4.00
Number of Profiles= 1
Profile Names=P100yr
River Rch & RM=lrlbrnch2,Main            ,2369.6
     394
River Rch & RM=lrlbrnch2,Main            ,1498.5
     402
River Rch & RM=lrlbrnch2,Main            ,1178.6
     467
River Rch & RM=lrlbrnch2,Main            ,278.2
     474
Boundary for River Rch & Prof#=lrlbrnch2,Main            , 1
Up Type= 0
Dn Type= 3
Dn Slope=0.022
DSS Import GetInterval= 0
DSS Import GetPeak= 0
DSS Import FillOption= 0

--- lrlbrnch2.g01 (geometry) ---

Geom Title=USGS 10m DEM
Program Version=4.00

River Reach=lrlbrnch2       ,Main
Reach XY= 30
     1621388.346      313530.289     1621415.066      313502.672
     1621495.209      313392.781     1621534.679      313313.398
     1621611.016      313201.686     1621624.421      313177.109
     1621775.233      313007.306     1621787.894      312987.198
     1621834.066      312900.875     1621874.903      312770.279
     1621895.336      312682.038     1621891.718      312636.645
     1621900.604      312612.836     1621927.356      312589.169
      1621938.61      312564.849     1622003.615      312497.343
     1622008.391      312440.019     1621961.483      312051.691
     1621958.323      311974.199     1621924.053      311799.953
     1621921.808      311762.457     1621913.275      311742.025
     1621902.087      311636.121     1621921.869      311563.829
     1621920.756       311533.93     1621911.037      311516.108
     1621890.805      311505.076     1621871.717      311488.963
     1621840.456      311437.416     1621799.766      311412.853

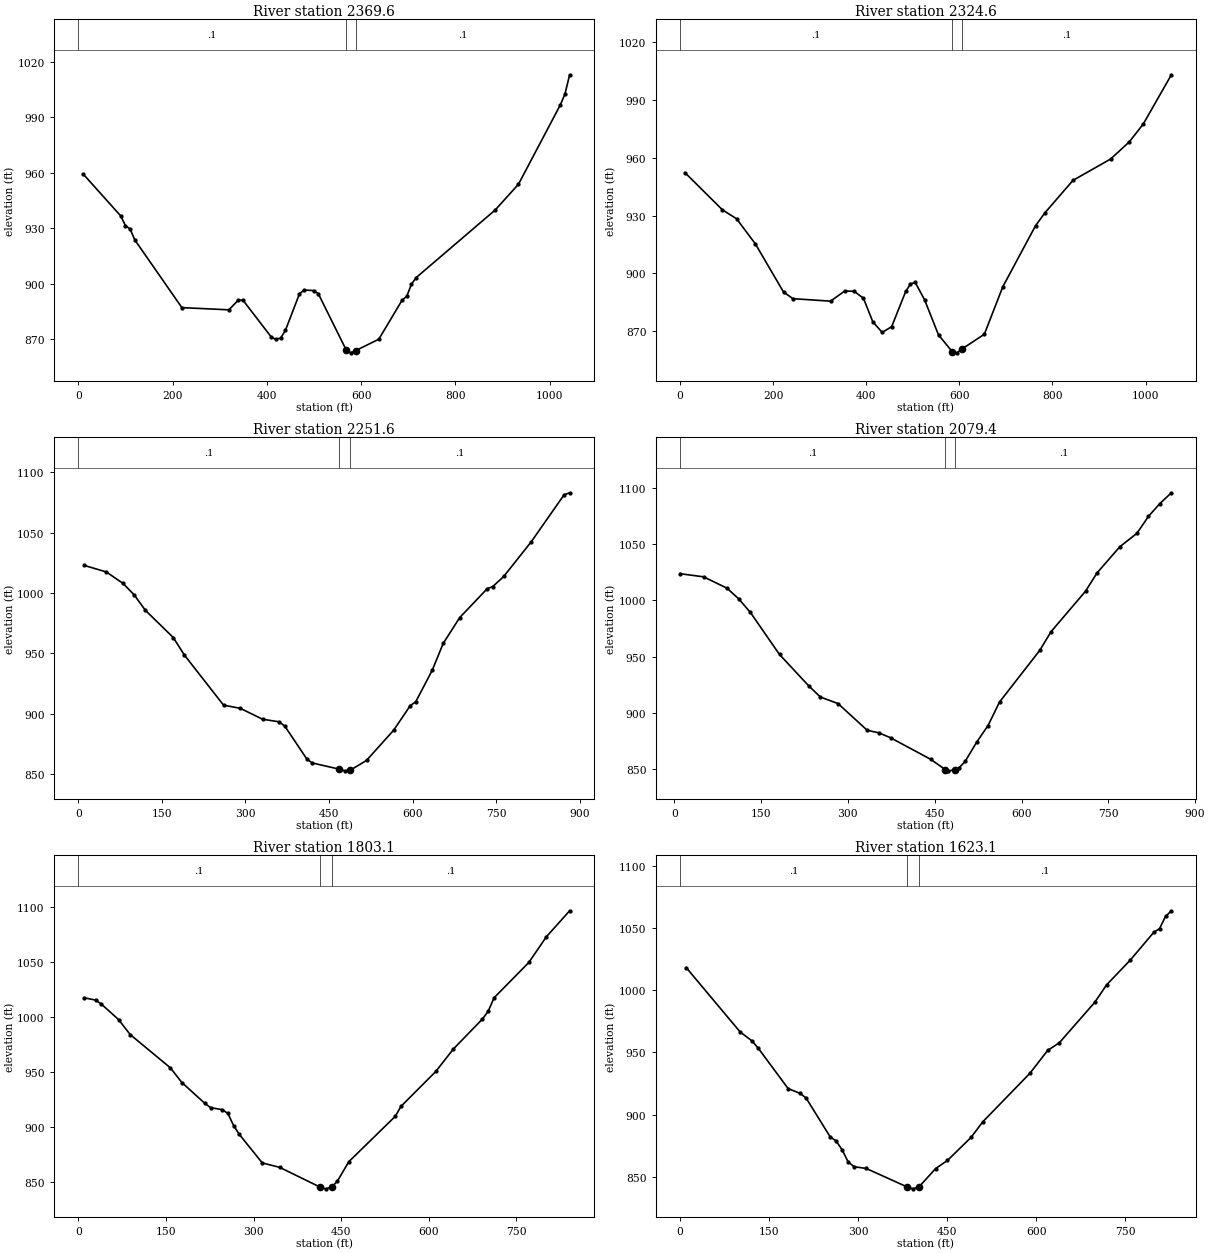
Type RM Length L Ch R = 1 ,2369.6  ,43.8,45,46.3
XS GIS Cut Line= 4
     1621688.745      314016.393     1621465.869       313570.01
     1621295.558      313451.424     1620980.588       313335.15
#Sta/Elev= 30
      10  959.36    89.8   936.7    99.8  931.48   109.8  929.58   119.7  923.74
   219.5  887.18   319.3  885.99   339.3  891.26   349.3  891.13   409.1  871.33
   419.1  869.97   429.1  870.78   439.1  874.84     469  894.66     479  896.71
   498.9  896.39   508.8  894.77     568  864.37     578  862.76     588  863.93
   637.3  870.12   686.7  891.18   696.6  893.29   706.5  899.79   716.3  903.34
   884.2   939.9   933.6  953.82  1022.5  996.71  1032.3 1002.63  1042.2 1012.94
#Mann= 3 , 0 , 0
       0      .1       0     568    .045       0     588      .1       0
Bank Sta=568,588
XS Rating Curve= 0 ,0
Exp/Cntr=0.3,0.1

Type RM Length L Ch R = 1 ,2324.6  ,74.9,73,71.1
XS GIS Cut Line= 4
      1621715.32        314005.7      1621467.61      313519.839
      1621358.38      313435.765     1621006.322      313314.364
#Sta/Elev= 30
    10.1  952.23    90.9  932.93   121.2  928.33   161.6  915.34   222.2  890.38
   242.4  886.97   323.2  885.68   353.5  890.91   373.7  890.82   393.9  887.18
   414.1  874.95   434.3   869.5   454.5  872.49   484.8  890.74   494.9  894.51
     505  895.44   525.2  886.43   555.2   868.2   584.6  859.59   594.6  858.94
   604.6  860.78   653.7  868.56   693.3  893.09   763.7  924.72   783.9  931.41
   844.2  948.19   924.8  959.19     965  968.06   995.2  977.33  1055.6 1002.82
#Mann= 3 , 0 , 0
       0      .1       0   584.6    .045       0   604.6      .1       0
Bank Sta=584.6,604.6
XS Rating Curve= 0 ,0
Exp/Cntr=0.3,0.1

Type RM Length L Ch R = 1 ,2251.6  ,173,172.2,171.5
XS GIS Cut Line= 4
     1621921.211      313575.744     1621560.719      313488.697
     1621397.032      313381.779     1621204.959      313131.044
#Sta/Elev= 30
      10 1022.91    50.1 1017.44    80.2 1007.92   100.2  998.45   120.3  985.67
   170.4  963.13   190.4   948.6   260.6   907.2   290.7  904.55   330.8  895.52
   360.8  893.36   370.9  889.66     410  862.74   419.7  859.34   468.4  854.21
   478.4  852.81   488.4  853.36   517.5  861.47   566.4  886.59     596  906.82
   605.8  909.96   635.5  936.18   655.2  958.37   684.8  979.68   734.2 1003.59
     744 1005.29   763.8 1013.68   813.1 1042.35   872.3 1081.35   882.2 1082.97
#Mann= 3 , 0 , 0
       0      .1       0   468.4    .045       0   488.4      .1       0
Bank Sta=468.4,488.4
XS Rating Curve= 0 ,0
Exp/Cntr=0.3,0.1

Type RM Length L Ch R = 1 ,2079.4  ,271.9,276.3,280.6
XS GIS Cut Line= 4
     1621939.375      313565.595     1621644.927      313335.375
     1621475.878      313231.926      1621216.08      313109.751
#Sta/Elev= 30
    10.1 1023.62    50.5 1020.87    90.9 1010.82   111.1 1001.37   131.3  989.33
   181.8   951.8   232.3  923.88   252.5  913.96   282.9  908.15   333.4  884.38
   353.6   882.1   373.8  877.71   443.1  858.56  468.61   849.3   472.9  848.32
  485.87  849.17   492.7  851.28   502.6   856.7   522.4  873.71   542.2  888.63
     562   909.5   631.4  955.35   651.2  972.17   710.6 1008.03   730.4 1024.24
     770 1047.64   799.6 1059.62   819.4 1074.63   839.2 1086.05     859  1095.6
#Mann= 3 , 0 , 0
    10.1      .1       0  468.61    .045       0  485.87      .1       0
Bank Sta=468.61,485.87
XS Rating Curve= 0 ,0
Exp/Cntr=0.3,0.1

Type RM Length L Ch R = 1 ,1803.1  ,184.1,180,175.9
XS GIS Cut Line= 4
     1622073.942      313286.369     1621793.034      313123.207
     1621666.878       313012.19     1621330.462      312921.357
#Sta/Elev= 30
     9.8 1017.33    29.5 1015.27    39.4 1011.54    68.9  997.46    88.6  983.92
   157.5  953.57   177.2  940.22   216.6   921.2   226.4  917.34   246.1   915.5
   255.9  912.15   265.8  901.04   275.6  892.96     315  866.98   344.6  863.01
   413.7  845.06   423.7  843.42   433.7  844.94   443.5  850.38   463.2  868.15
   542.7  909.42   552.6  918.56   612.4  950.42   642.2   970.7     692  997.98
     702 1005.22   711.9  1017.3   771.7 1049.63   801.5 1072.87   841.4 1096.55
#Mann= 3 , 0 , 0
       0      .1       0   413.7    .045       0   433.7      .1       0
Bank Sta=413.7,433.7
XS Rating Curve= 0 ,0
Exp/Cntr=0.3,0.1

Type RM Length L Ch R = 1 ,1623.1  ,129.6,124.5,119.4
XS GIS Cut Line= 4
     1622092.157      313205.693     1621852.072      312932.066
     1621795.581       312896.76     1621492.532      312640.051
#Sta/Elev= 30
    10.1 1018.16   101.1  966.38   121.3  959.09   131.5  953.39     182  920.86
   202.2  917.01   212.3  913.26   252.8  882.14   262.9  878.75     273  871.65
   283.1  861.94   293.2  858.12   313.5   856.7   382.6  841.83   392.6  840.32
   402.6  841.93   430.6  856.66   450.5  863.14   490.2  881.64   510.1  894.23
   589.5  933.21   619.3  951.52   639.1  957.74   698.7  990.19   718.6  1004.2
   758.3    1024     798 1046.34   807.9 1049.46   817.9 1059.16   827.8 1063.74
#Mann= 3 , 0 , 0
       0      .1       0   382.6    .045       0   402.6      .1       0
Bank Sta=382.6,402.6
XS Rating Curve= 0 ,0
Exp/Cntr=0.3,0.1

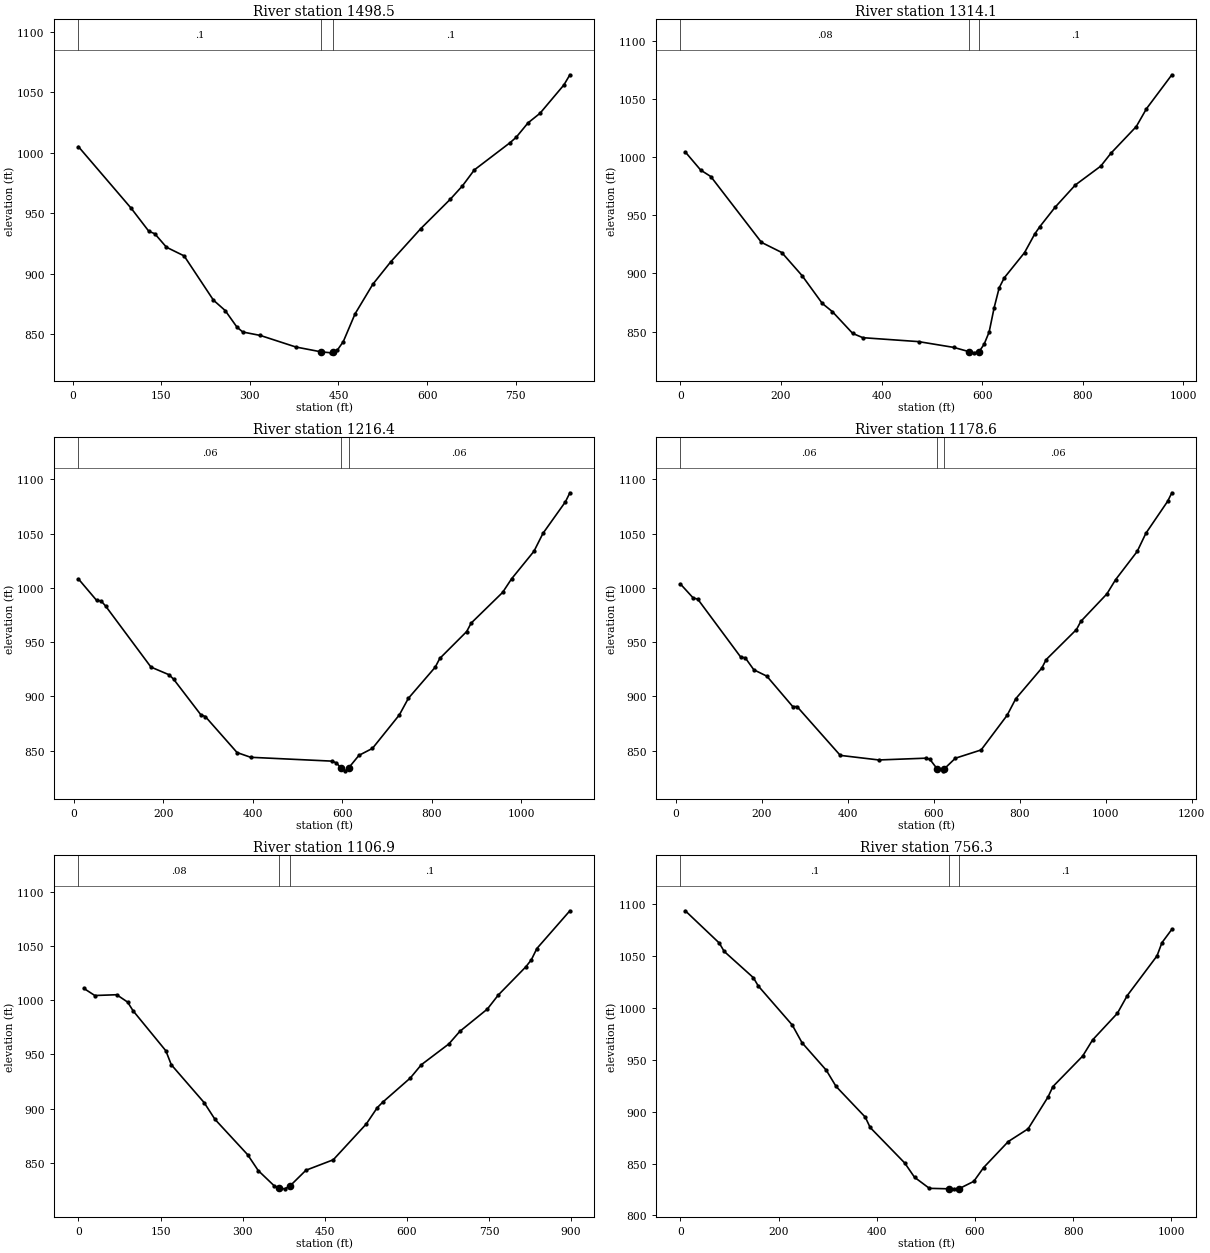
Type RM Length L Ch R = 1 ,1498.5  ,186.3,184.5,182.9
XS GIS Cut Line= 4
     1622115.017      313137.861     1621952.637      312830.408
     1621802.149      312774.531     1621503.159      312626.929
#Sta/Elev= 30
     9.9 1005.11    99.3  954.05   129.1  935.05   139.1  933.06   158.9  921.87
   188.8   914.7   238.4  878.08   258.3  869.48   278.2  855.76   288.1  851.71
   317.9  848.84   377.8  839.31  420.46   835.3     438  834.47   440.3  834.83
     448  836.67   458.1  843.68   478.1  866.74   508.2  891.25   538.5   909.8
   589.1  937.16   639.6  961.75   659.8  972.62     680  985.88   740.6 1008.45
   750.7 1012.81   770.9 1024.81   791.1  1032.7   831.6 1056.21   841.7 1064.59
#Mann= 3 , 0 , 0
     9.9      .1       0  420.46    .045       0   440.3      .1       0
Bank Sta=420.46,440.3
XS Rating Curve= 0 ,0
Exp/Cntr=0.3,0.1

Type RM Length L Ch R = 1 ,1314.1  ,78.3,97.7,117
XS GIS Cut Line= 4
      1622194.93       313087.52     1622010.427      312651.335
     1621837.277      312601.188     1621514.633      312582.264
#Sta/Elev= 30
    10.1  1004.1    40.3  988.73    60.5  983.15   161.2  926.61   201.5  917.92
   241.8  898.11   282.1  874.17   302.3  867.07   342.6  848.38   362.8  844.74
   473.6  841.37   543.7  836.38   573.8  832.73   583.8  831.73   593.8  832.72
   603.8   839.1   613.8  849.61   623.8   870.6   633.8  887.61   643.9  896.19
   684.2  917.83   704.4  933.78   714.5  940.09   744.8  956.74   785.2  975.93
   835.7  992.11   855.9 1003.17   906.4 1026.14   926.6 1041.44   977.1 1070.59
#Mann= 3 , 0 , 0
       0     .08       0   573.8    .045       0   593.8      .1       0
Bank Sta=573.8,593.8
XS Rating Curve= 0 ,0
Exp/Cntr=0.3,0.1

Type RM Length L Ch R = 1 ,1216.4  ,35.6,37.8,39.9
XS GIS Cut Line= 4
     1622215.237       313092.93     1622018.568      312647.984
     1621927.834      312491.274     1621493.624      312571.484
#Sta/Elev= 30
    10.1 1008.27    50.7  988.55    60.8  988.01    70.9   983.3   172.3  927.08
   212.8  920.01     223   915.9   283.8  883.17   293.9   881.5   364.9  848.34
   395.3  843.99     577  840.45   587.1  838.81   597.2  834.05   607.2  831.51
  614.27  834.18   637.4  845.77   667.6   852.2   727.8  883.07   747.8  898.25
     808  927.03   818.1  935.02   878.3  959.82   888.3  967.58   958.6  995.83
   978.7 1008.38  1028.8 1033.78  1048.9 1050.25  1099.1  1079.3  1109.1 1087.63
#Mann= 3 , 0 , 0
    10.1     .06       0   597.2    .045       0  614.27     .06       0
Bank Sta=597.2,614.27
XS Rating Curve= 0 ,0
Exp/Cntr=0.3,0.1

Type RM Length L Ch R = 1 ,1178.6  ,100.1,71.7,43.3
XS GIS Cut Line= 4
     1622234.078      313082.947      1622069.76      312693.912
     1621958.249      312462.061     1621493.541      312556.718
#Sta/Elev= 30
    10.1  1003.7    40.2  990.65    50.3  989.81   150.8  936.13   160.9   935.7
     181  924.59   211.2  918.74   271.5  890.71   281.5  890.71   382.1  845.71
   471.8  841.49   580.6  843.12   590.5  842.17  607.52  833.32   620.2  831.46
   623.6  833.09   649.9  843.08   709.9  850.72   770.4  882.66   790.6  897.98
   851.1  926.16   861.2  933.97   931.8  961.71   941.9   969.2  1002.5  994.51
  1022.7 1007.59  1073.1 1033.69  1093.3 1050.42  1143.7 1079.76  1153.8 1087.76
#Mann= 3 , 0 , 0
    10.1     .06       0  607.52    .045       0   623.6     .06       0
Bank Sta=607.52,623.6
XS Rating Curve= 0 ,0
Exp/Cntr=0.3,0.1

Type RM Length L Ch R = 1 ,1106.9  ,354.4,350.6,346.8
XS GIS Cut Line= 4
     1622386.057      312440.338     1622087.067      312455.477
     1621961.226      312451.693     1621497.602      312542.525
#Sta/Elev= 30
      10    1011    29.9 1004.47    69.9 1005.19    89.8  998.41    99.8  990.39
   159.7  953.41   169.6  940.56   229.5  905.65   249.5  890.06   309.1  857.45
   328.4  842.82   357.5  828.77   366.8  826.57   376.8  825.93   386.8  828.77
   415.6  843.11   465.5  852.77   525.8  885.84   545.9  900.93   555.9  905.99
   606.2  928.28   626.3  940.51   676.6  959.74   696.7  971.38   746.9  991.94
     767 1004.97   817.3 1030.99   827.3 1037.46   837.4 1047.88   897.7 1082.72
#Mann= 3 , 0 , 0
       0     .08       0   366.8    .045       0   386.8      .1       0
Bank Sta=366.8,386.8
XS Rating Curve= 0 ,0
Exp/Cntr=0.3,0.1

Type RM Length L Ch R = 1 ,756.3   ,119,120.7,122.3
XS GIS Cut Line= 4
     1622487.419      312146.022     1622115.679      312087.149
     1621836.453      312120.791     1621508.447      312221.716
#Sta/Elev= 30
     9.9 1093.59    79.2 1062.48    89.1 1054.45   148.6 1029.13   158.5 1021.17
   227.8   983.5   247.6   966.5   297.1  939.94   316.9   924.4   376.4  894.79
   386.4   884.8   456.7  850.63   476.8  836.81     507  826.16   547.2   825.7
   557.2  825.68   567.2  825.76   597.4  832.87   617.4  846.14   667.7  871.26
   708.1  883.53   748.5  914.09   758.6  924.23   819.1  953.57   839.3  969.13
   889.8  994.79     910 1011.92   970.5 1050.09   980.6 1062.86  1000.8 1075.75
#Mann= 3 , 0 , 0
       0      .1       0   547.2    .045       0   567.2      .1       0
Bank Sta=547.2,567.2
XS Rating Curve= 0 ,0
Exp/Cntr=0.3,0.1

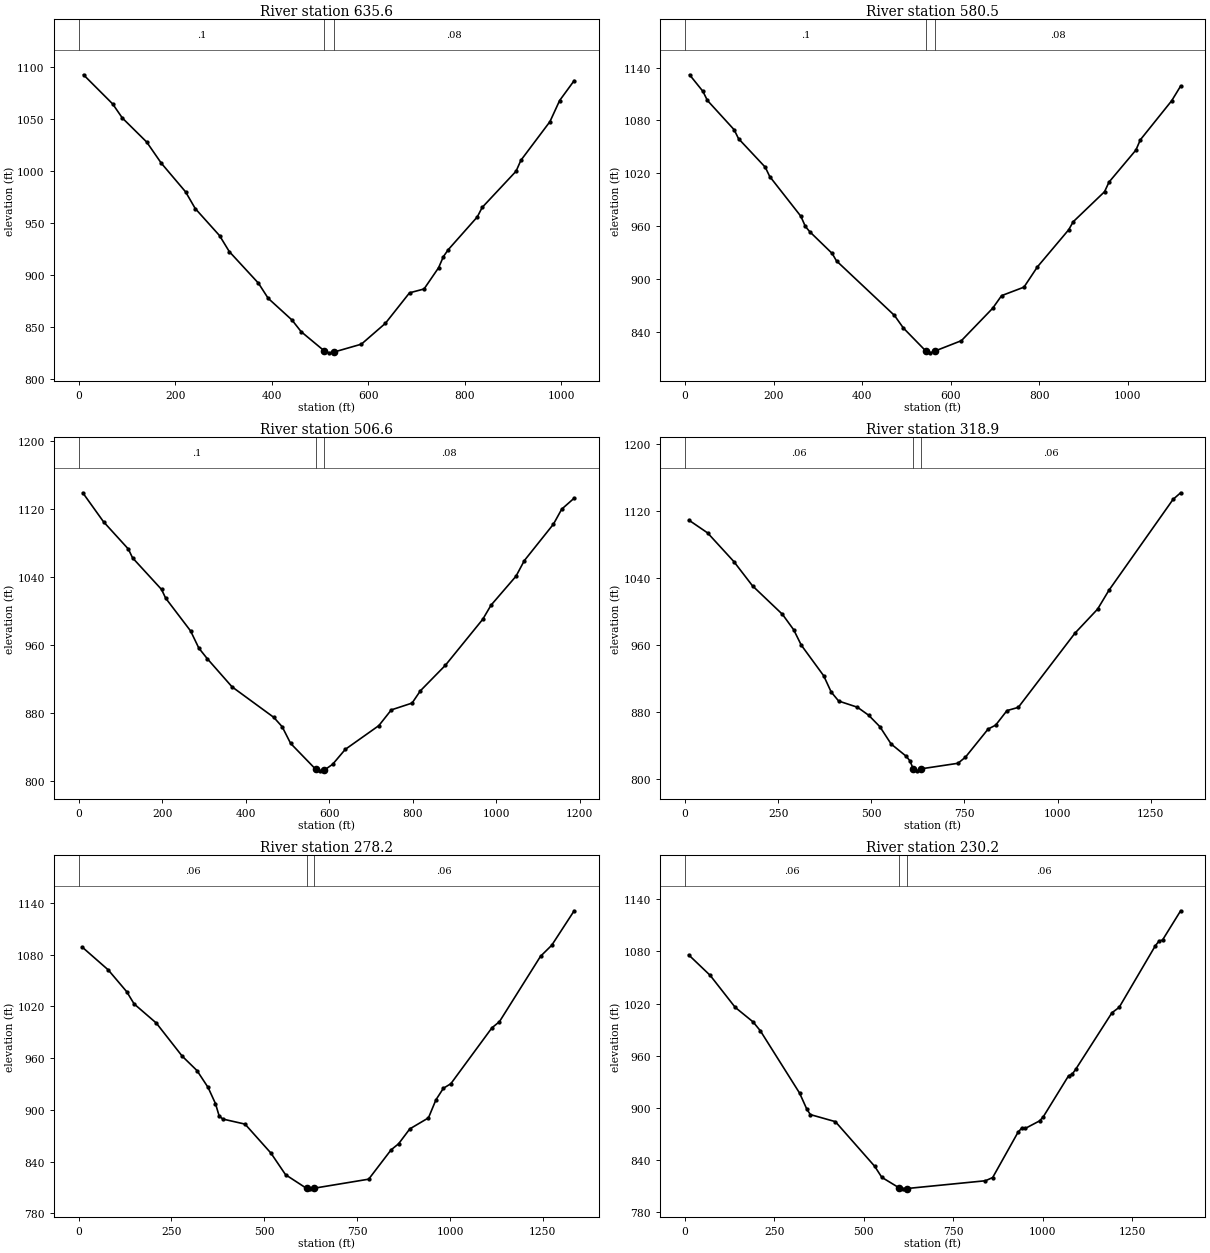
Type RM Length L Ch R = 1 ,635.6   ,56.1,55.1,54.1
XS GIS Cut Line= 4
     1622471.408      312008.605     1622049.416      311979.747
     1621877.212      311989.209     1621488.336      312176.078
#Sta/Elev= 30
    10.1  1092.1    70.5 1064.09    90.6 1050.54     141 1027.47   171.2 1007.18
   221.6  979.57   241.7  963.46   292.1  937.44   312.2  922.13   372.6  891.77
   392.8   877.2   442.1  856.36   461.3  845.05   508.8  826.75   518.8  824.79
   528.8   825.5   585.9  833.12   635.6  853.12   685.7  882.47   715.8  886.18
   745.9  906.59     756  917.37     766  923.99   826.2  955.49   836.2  964.55
   906.5   999.4   916.5  1009.9   976.7 1047.07   996.8 1067.37  1026.9 1086.49
#Mann= 3 , 0 , 0
       0      .1       0   508.8    .045       0   528.8     .08       0
Bank Sta=508.8,528.8
XS Rating Curve= 0 ,0
Exp/Cntr=0.3,0.1

Type RM Length L Ch R = 1 ,580.5   ,73.3,73.9,74.5
XS GIS Cut Line= 4
     1622499.084      311912.214     1622096.724      311916.472
     1621805.776      311944.148     1621439.608      312159.165
#Sta/Elev= 30
    10.1 1131.79    40.2 1113.04    50.3 1102.75   110.7 1069.54   120.7 1059.37
   181.1    1027   191.1 1016.48   261.5   971.4   271.6  959.91   281.7  953.84
     332  929.37     342   920.8   472.9  858.99   493.1  844.69   543.6  818.74
   553.6   816.6   563.6   818.5   624.1  830.39   694.6  867.05   714.9  881.44
   765.4  891.06   795.7  913.98   866.5  956.15   876.6  965.16   947.4  999.23
   957.5 1010.14  1018.2 1046.41  1028.3 1058.09  1099.1 1102.38  1119.3 1119.02
#Mann= 3 , 0 , 0
       0      .1       0   543.6    .045       0   563.6     .08       0
Bank Sta=543.6,563.6
XS Rating Curve= 0 ,0
Exp/Cntr=0.3,0.1

Type RM Length L Ch R = 1 ,506.6   ,189.4,187.7,186.1
XS GIS Cut Line= 4
     1622506.316      311898.467     1622092.524      311846.743
     1621811.196      311866.928     1621407.496      312140.687
#Sta/Elev= 30
     9.9 1139.38    59.6  1105.2   119.1 1073.02   129.1 1062.69   198.6 1025.38
   208.5 1015.07   268.1   976.5   287.9  956.22   307.8  943.94   367.4  910.57
   467.4  874.58   487.5  863.52   507.7  843.89   568.2  813.16   578.2  811.53
   588.2  812.33   608.4  819.28   638.6  836.84     719  864.85   748.8  883.37
   798.6  891.43   818.5  905.91   878.2  935.89   967.8  990.19   987.7 1006.87
  1047.5 1041.02  1067.4 1059.38  1137.1 1102.36    1157  1120.1  1186.8 1133.04
#Mann= 3 , 0 , 0
       0      .1       0   568.2    .045       0   588.2     .08       0
Bank Sta=568.2,588.2
XS Rating Curve= 0 ,0
Exp/Cntr=0.3,0.1

Type RM Length L Ch R = 1 ,318.9   ,38.8,40.7,42.6
XS GIS Cut Line= 4
     1622508.445      311821.591     1621934.751       311669.61
     1621807.018      311687.292     1621351.593      312090.303
#Sta/Elev= 30
    10.1 1108.89    60.4 1093.67   130.8 1059.55   181.1 1030.52   261.5  996.56
   291.7  978.12   311.8  959.99   372.2  923.33   392.3  903.99   412.4  893.24
   462.7  885.88   492.9  876.34   523.1  862.63   553.2  842.04   593.5  827.51
   603.4  822.12   613.2  811.92   623.2  810.05   633.2  812.41   732.6  819.05
   752.8  826.36   813.7  859.87   833.9  864.53   864.3  881.86   894.7   885.7
  1046.8  974.13  1107.6 1002.81    1138 1025.25  1310.3 1133.64  1330.6 1141.49
#Mann= 3 , 0 , 0
       0     .06       0   613.2    .045       0   633.2     .06       0
Bank Sta=613.2,633.2
XS Rating Curve= 0 ,0
Exp/Cntr=0.3,0.1

Type RM Length L Ch R = 1 ,278.2   ,43.8,47.9,52
XS GIS Cut Line= 4
     1622497.646       311790.91     1621974.447       311628.79
     1621821.877      311638.016     1621355.872      312067.741
#Sta/Elev= 30
      10 1088.53    79.7 1062.26   129.5 1036.97   149.4 1022.81   209.1 1000.66
   278.9  962.26   318.7  945.57   348.6  926.01   368.5  907.27   378.4  892.98
   388.4  889.34   448.2  883.47   517.9  849.86   557.3  824.82   614.2   808.9
   624.2  808.46   634.2  809.19   781.1  819.66   841.5  853.67   861.6  860.66
   891.8  877.93   942.1  890.72   962.2  911.63   982.3  925.03  1002.4  930.33
  1113.1  995.14  1133.2 1002.18  1243.9 1078.02  1274.1 1090.82  1334.5 1130.77
#Mann= 3 , 0 , 0
       0     .06       0   614.2    .045       0   634.2     .06       0
Bank Sta=614.2,634.2
XS Rating Curve= 0 ,0
Exp/Cntr=0.3,0.1

Type RM Length L Ch R = 1 ,230.2   ,56.7,55.3,57.8
XS GIS Cut Line= 4
     1622490.783        311772.6     1622011.569      311596.548
     1621804.357      311575.732     1621343.603      312058.554
#Sta/Elev= 30
      10 1075.94    70.1 1052.41   140.1 1015.66   190.2  998.92   210.2  988.89
   320.3   917.1   340.4  898.76   350.4  892.44   420.4  884.31   530.4  833.01
   550.2  820.36   599.7  808.02   609.7  807.12   619.7  807.45   840.1  816.41
   860.4  820.12   931.1  871.99   941.2  876.74   951.4   876.5   991.8  885.23
  1001.9  889.87  1072.7  937.02  1082.8  938.84  1092.9  944.63    1194  1009.4
  1214.3 1015.68  1315.4 1086.41  1325.5 1091.68  1335.6 1093.06  1386.2 1126.61
#Mann= 3 , 0 , 0
       0     .06       0   599.7    .045       0   619.7     .06       0
Bank Sta=599.7,619.7
XS Rating Curve= 0 ,0
Exp/Cntr=0.3,0.1

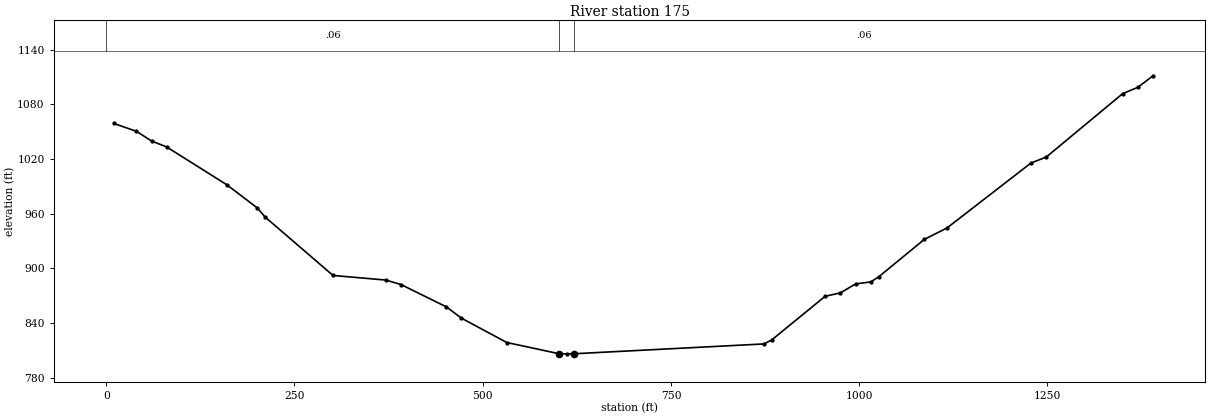
Type RM Length L Ch R = 1 ,175     ,202.4,175,143.6
XS GIS Cut Line= 4
       1622473.3      311749.827       1621975.7      311534.797
      1621836.68      311529.832     1621341.679      312037.464
#Sta/Elev= 30
      10    1059    40.2 1050.32    60.2 1039.74    80.3 1033.19   160.6  991.46
   200.8  966.14   210.8  956.44   301.2  892.16   371.4  887.09   391.5  882.17
   451.7   857.7   471.8  845.25     532  818.57   601.6  806.23   611.6  806.13
   621.6  806.24   873.6  817.01   883.8  821.41   954.7  869.26   974.9  873.04
   995.2  882.86  1015.4  885.08  1025.6   890.5  1086.3  931.63  1116.7  944.36
  1228.1  1015.6  1248.4 1022.12  1349.7 1091.62  1369.9  1098.6  1390.2  1111.3
#Mann= 3 , 0 , 0
       0     .06       0   601.6    .045       0   621.6     .06       0
Bank Sta=601.6,621.6
XS Rating Curve= 0 ,0
Exp/Cntr=0.3,0.1

Chan Stop Cuts=-1
Use User Specified Reach Order=0